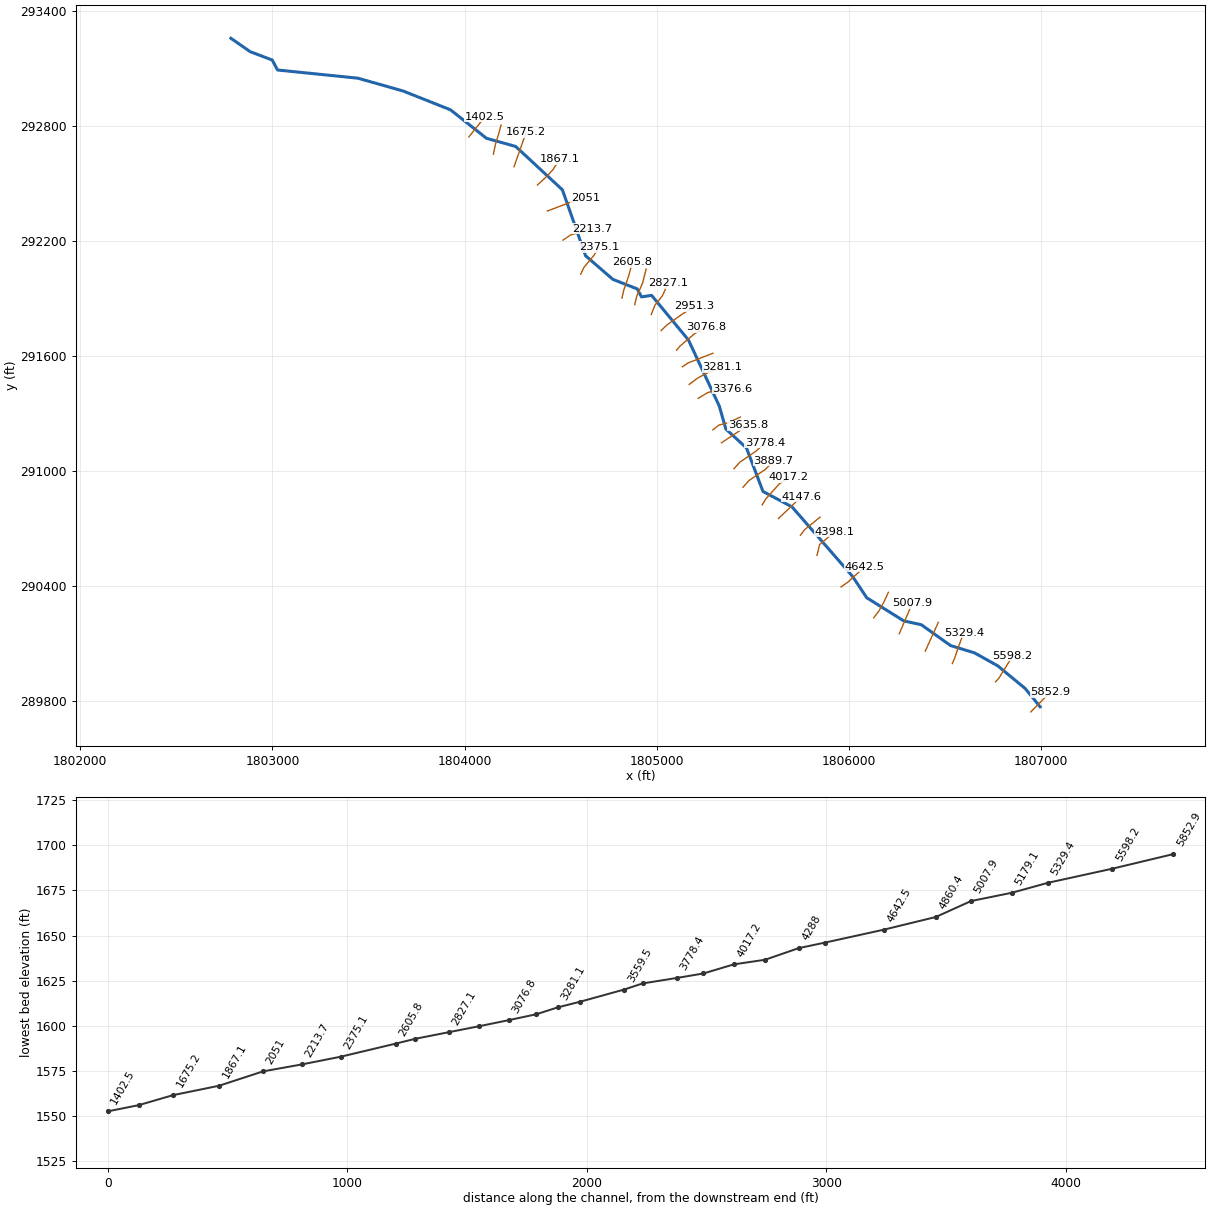
--- LACEYBR.prj (project) ---

Proj Title=LACEYBR
Current Plan=p01
Default Exp/Contr=0,0
English Units
Geom File=g01
Flow File=f01
Plan File=p01
BEGIN DESCRIPTION:
END DESCRIPTION:
DSS Export Rating Curves= 0
DSS Export Rating Curve Sorted= 0
DSS Export Volume Flow Curves= 0
DXF OffsetX= 0
DXF OffsetY= 0
DXF ScaleX= 0
DXF ScaleY= 0

--- LACEYBR.p01 (plan) ---

Plan Title=Floodplain
Program Version=4.00
Geom File=g01
Flow File=f01
K Sum by GR=0
Std Step Tol=0.01
Critical Tol=0.01
Num of Std Step Trials=20
Max Error Tol=0.3
Flow Tol Ratio=0.001
Split Flow NTrial=30
Split Flow Tol=0.02
Split Flow Ratio=0.02
Log Output Level=0
Friction Slope Method=1
Unsteady Friction Slope Method=2
Unsteady Bridges Friction Slope Method=1
Global Log Level=0
CheckData=False
Run HTab=0
Run UNet=0
Run PostProcess=0
UNET Theta=0
UNET Theta Warmup=0
UNET ZTol=0
UNET ZSATol=0
UNET MxIter=0
UNET MaxInSteps=0
UNET DtIC=0
UNET DtMin=0
UNET MaxCRTS=0
UNET WFStab=0
UNET SFStab=0
UNET WFX=0
UNET SFX=0
UNET DSS MLevel=0
UNET DZMax Abort=0
UNET Convert EG Bridges=0
UNET Use Existing IB Tables=0
UNET Froude Limit=0
UNET Froude Power=0
Write IC File=0
Echo Input=False
Echo Output=False
Write Detailed=0

--- LACEYBR.f01 (steady flow) ---

Flow Title=NFF Regression Equation
Program Version=4.00
Number of Profiles=1
Profile Names=P100yr
River Rch & RM=LACEYBR,Main      ,5852.9
935.6113
River Rch & RM=LACEYBR,Main      ,3889.7
1023.650
River Rch & RM=LACEYBR,Main      ,2375.1
1133.038
River Rch & RM=LACEYBR,Main      ,547.8
1181.165
Boundary for River Rch & Prof#=LACEYBR,Main      ,1
Up Type=0
Dn Type=3
Dn Slope=0.034303

--- LACEYBR.g01 (geometry) ---

Geom Title=USGS 10m DEM
Program Version=4.10

River Reach=LACEYBR         ,Main
Reach XY= 30
     1806995.997      289771.488     1806918.708      289866.733
     1806775.086      289985.204     1806654.834      290052.538
     1806529.923      290090.792     1806377.334      290199.338
     1806286.189      290219.303      1806093.48      290339.963
     1806019.695      290451.074     1805704.504      290813.463
      1805553.55      290893.782     1805467.612      291120.345
     1805359.973      291219.303     1805326.119        291338.4
     1805165.529      291683.018     1804973.689      291915.657
     1804920.737      291907.845     1804899.112       291949.12
     1804772.299      291998.991     1804629.939      292122.254
     1804509.279      292466.004     1804266.223      292691.699
     1804114.314      292734.234     1803926.814      292882.671
     1803680.286      292980.761     1803444.175      293047.602
      1803026.64      293090.136     1802998.862       293142.22
     1802884.279      293185.622      1802783.58      293255.575

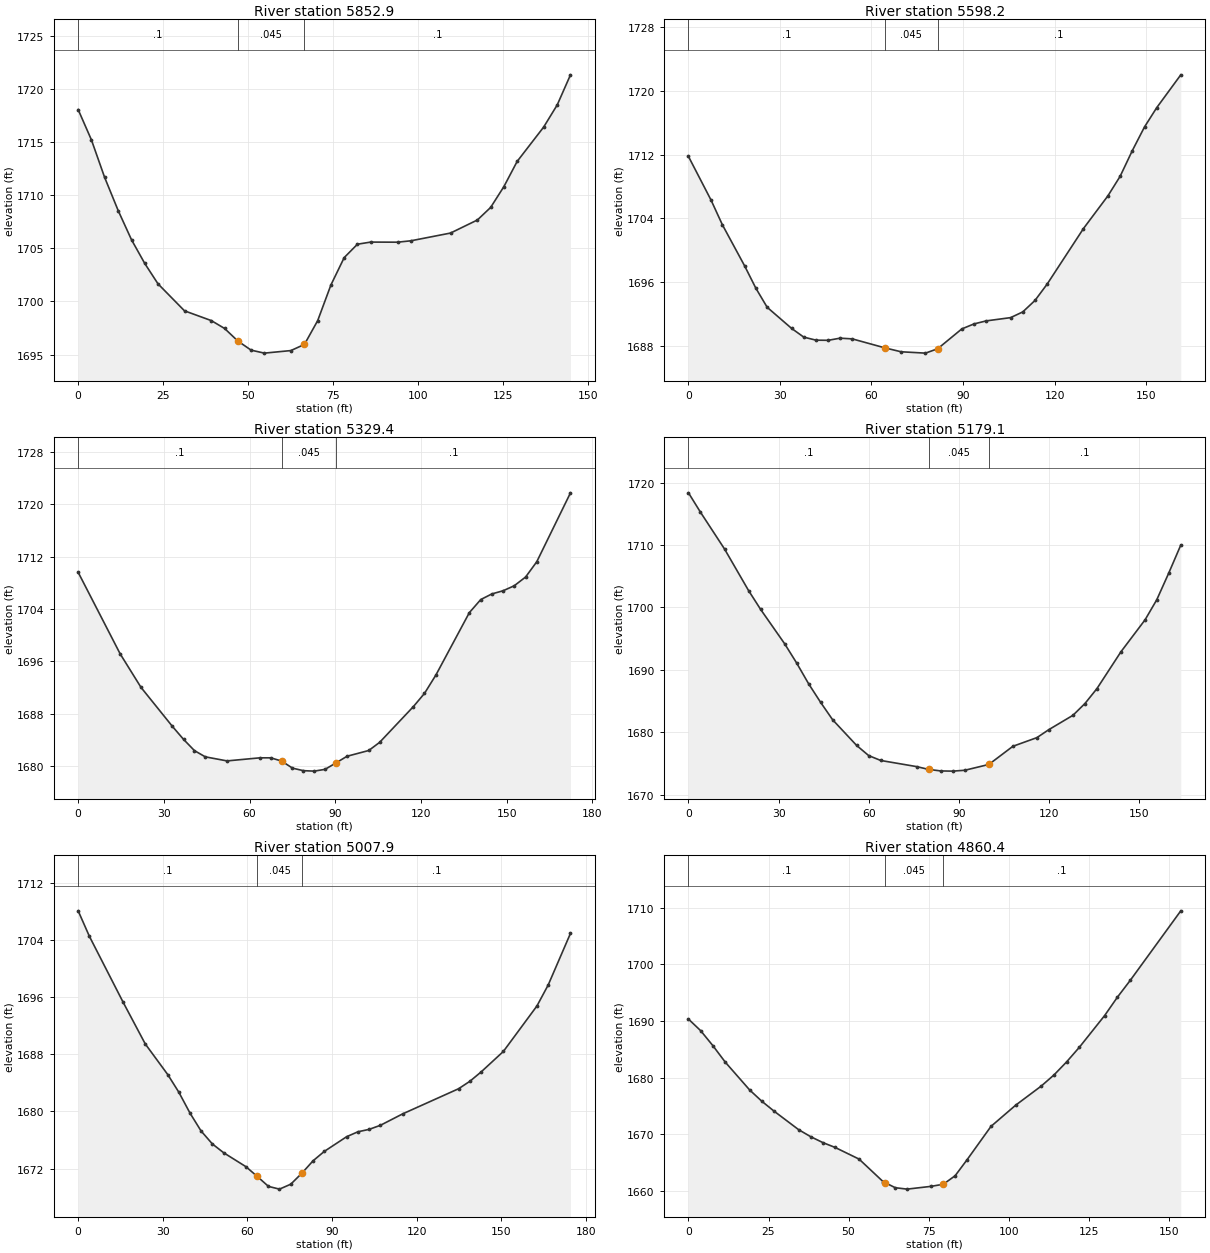
Type RM Length L Ch R = 1 ,5852.9  ,249.4,254.7,259.6
XS GIS Cut Line= 2
     1806947.704      289745.089     1807049.267      289848.388
#Sta/Elev= 30
       0 1718.06     3.9 1715.21     7.8 1711.67    11.8 1708.54    15.7 1705.81
    19.6 1703.58    23.5 1701.66    31.3 1699.12    39.2  1698.2    43.1 1697.46
      47 1696.28    50.9 1695.42    54.8 1695.14    62.6 1695.38    66.6 1695.96
    70.5  1698.2    74.4 1701.56    78.3 1704.13    82.2 1705.39    86.1 1705.59
      94 1705.58    97.9 1705.71   109.6 1706.44   117.5 1707.67   121.4 1708.85
   125.3 1710.81   129.2 1713.18     137 1716.41     141  1718.5   144.9 1721.33
#Mann= 3 , 0 , 0
       0      .1       0      47    .045       0    66.6      .1       0
Bank Sta=47,66.6
XS Rating Curve= 0 ,0
Exp/Cntr=0.3,0.1

Type RM Length L Ch R = 1 ,5598.2  ,262.8,268.9,273.3
XS GIS Cut Line= 3
     1806764.545      289902.207     1806781.906      289921.305
     1806853.086      290036.756
#Sta/Elev= 30
       0 1711.77     7.4 1706.29    11.1  1703.2    18.4 1698.03    22.1 1695.21
    25.8 1692.82    33.8 1690.17    37.8 1689.07    41.8 1688.69    45.8 1688.67
    49.7 1688.94    53.7 1688.85    64.3 1687.73    69.7 1687.23    77.7 1687.06
    81.7 1687.61    89.6  1690.1    93.6 1690.73    97.6 1691.11   105.6 1691.52
   109.6 1692.24   113.6 1693.68   117.6 1695.74   129.5 1702.72   137.5 1706.82
   141.5 1709.27   145.5  1712.5   149.5 1715.48   153.5  1717.9   161.4 1722.03
#Mann= 3 , 0 , 0
       0      .1       0    64.3    .045       0    81.7      .1       0
Bank Sta=64.3,81.7
XS Rating Curve= 0 ,0
Exp/Cntr=0.3,0.1

Type RM Length L Ch R = 1 ,5329.4  ,152.4,150.3,148.3
XS GIS Cut Line= 4
      1806538.85      289996.825     1806551.871      290027.207
     1806575.308      290095.784     1806598.746      290158.284
#Sta/Elev= 30
       0  1709.6    14.7 1697.15      22 1692.03      33 1686.07    36.9 1684.09
    40.7 1682.38    44.5 1681.43    52.1 1680.81    63.6 1681.28    67.4 1681.28
    71.2 1680.79      75 1679.71    78.8 1679.32    82.6 1679.25    86.4 1679.52
    90.3 1680.52    94.1 1681.52   101.7  1682.4   105.5 1683.64   117.3 1689.09
   121.2 1691.11   125.2 1693.92   136.9 1703.44   140.9 1705.44   144.8  1706.3
   148.7 1706.78   152.6 1707.54   156.6 1708.88   160.5 1711.21   172.3 1721.73
#Mann= 3 , 0 , 0
       0      .1       0    71.2    .045       0    90.3      .1       0
Bank Sta=71.2,90.3
XS Rating Curve= 0 ,0
Exp/Cntr=0.3,0.1

Type RM Length L Ch R = 1 ,5179.1  ,170.7,171.2,171.5
XS GIS Cut Line= 2
     1806398.225       290061.93     1806465.933      290211.235
#Sta/Elev= 30
       0 1718.36       4 1715.25      12 1709.36      20  1702.7      24 1699.69
      32 1694.18      36 1691.09      40 1687.75      44 1684.77      48 1681.98
      56 1677.86      60 1676.24      64 1675.46      76 1674.47      80 1674.02
      84 1673.78      88 1673.75      92 1673.89     100 1674.82     108 1677.73
     116 1679.12     120 1680.41     128  1682.7     132 1684.59     136 1686.99
     144  1692.9     152    1698   155.9 1701.22   159.9 1705.51   163.9 1709.99
#Mann= 3 , 0 , 0
       0      .1       0      80    .045       0     100      .1       0
Bank Sta=80,100
XS Rating Curve= 0 ,0
Exp/Cntr=0.3,0.1

Type RM Length L Ch R = 1 ,5007.9  ,149.5,147.5,145
XS GIS Cut Line= 2
     1806262.808      290152.207     1806331.385      290312.798
#Sta/Elev= 30
       0 1708.07       4 1704.49    15.9 1695.32    23.8 1689.45    31.8 1685.15
    35.7  1682.7    39.7 1679.75    43.6 1677.27    47.6 1675.46    51.6 1674.23
    59.5 1672.28    63.5 1670.92    67.5 1669.52    71.4 1669.14    75.4 1669.83
    79.4 1671.39    83.3  1673.1    87.3 1674.42    95.2 1676.47    99.2 1677.16
   103.2  1677.5   107.2 1678.07   115.1 1679.67   134.9 1683.18   138.9 1684.22
   142.9 1685.53   150.8  1688.4   162.7 1694.76   166.7  1697.7   174.6 1704.92
#Mann= 3 , 0 , 0
       0      .1       0    63.5    .045       0    79.4      .1       0
Bank Sta=63.5,79.4
XS Rating Curve= 0 ,0
Exp/Cntr=0.3,0.1

Type RM Length L Ch R = 1 ,4860.4  ,225.3,217.9,210.2
XS GIS Cut Line= 4
     1806129.996      290235.541     1806157.774      290271.999
     1806182.947      290318.006     1806206.385      290368.353
#Sta/Elev= 30
       0 1690.31     3.8 1688.27     7.6 1685.64    11.5 1682.71    19.1 1677.81
    22.9 1675.82    26.7 1674.08    34.4  1670.8    38.2 1669.55      42 1668.51
    45.8 1667.66    53.3  1665.6    60.8 1661.62    61.4 1661.45    64.6 1660.55
    68.3  1660.3    75.8 1660.79    79.6 1661.16    83.3 1662.66      87 1665.46
    94.5 1671.37   102.2 1675.11   110.2 1678.49   114.2 1680.46   118.1 1682.74
   122.1 1685.33     130 1690.93     134 1694.18     138 1697.14   153.8 1709.42
#Mann= 3 , 0 , 0
       0      .1       0    61.4    .045       0    79.6      .1       0
Bank Sta=61.4,79.6
XS Rating Curve= 0 ,0
Exp/Cntr=0.3,0.1

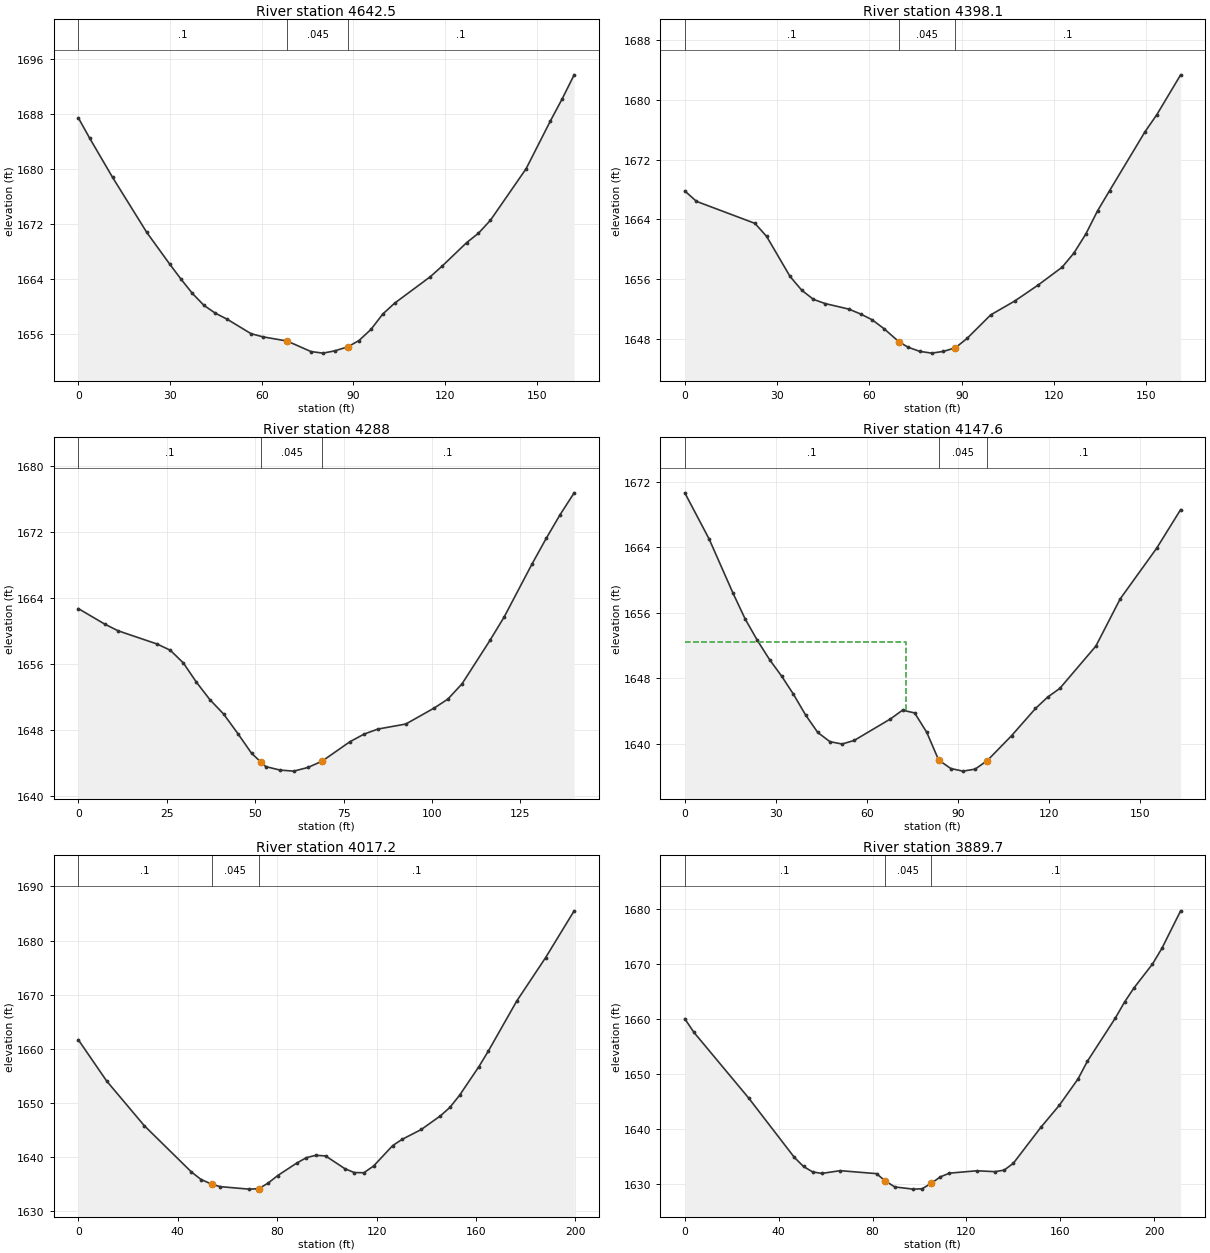
Type RM Length L Ch R = 1 ,4642.5  ,243.5,244.3,243.6
XS GIS Cut Line= 3
     1805959.857      290396.131     1805996.315      290422.173
     1806083.121      290501.166
#Sta/Elev= 30
       0  1687.5     3.7 1684.55    11.2 1678.84    22.4 1670.82    29.9 1666.21
    33.6 1664.02    37.3 1661.96    41.1 1660.21    44.8 1659.08    48.7 1658.19
    56.5 1656.09    60.4 1655.63    68.3 1655.02    76.1 1653.49      80 1653.26
    83.9 1653.59    88.2 1654.19    91.8 1655.09    95.7  1656.7    99.6 1658.95
   103.5 1660.54   115.2  1664.4   119.1 1665.96     127 1669.33   130.9 1670.71
   134.8 1672.59   146.5 1680.11   154.4 1687.03   158.3 1690.28   162.2 1693.76
#Mann= 3 , 0 , 0
       0      .1       0    68.3    .045       0    88.2      .1       0
Bank Sta=68.3,88.2
XS Rating Curve= 0 ,0
Exp/Cntr=0.3,0.1

Type RM Length L Ch R = 1 ,4398.1  ,111.9,110.1,109.4
XS GIS Cut Line= 3
     1805834.857      290561.062     1805847.878      290616.617
     1805926.871      290684.325
#Sta/Elev= 30
       0 1667.81     3.8 1666.42    22.8 1663.48    26.6 1661.73    34.2 1656.39
      38 1654.55    41.8 1653.33    45.6 1652.77    53.3 1652.03    57.1 1651.38
    60.9  1650.6    64.8 1649.39    69.6 1647.66    72.5 1646.95    76.3 1646.39
    80.2 1646.15      84 1646.38    87.9 1646.86    91.7 1648.11    99.4 1651.26
   107.2 1653.11   114.9 1655.27   122.6 1657.63   126.4  1659.5   130.3 1662.06
   134.1 1665.15     138 1667.84   149.5  1675.7   153.4 1678.02   161.1 1683.32
#Mann= 3 , 0 , 0
       0      .1       0    69.6    .045       0    87.9      .1       0
Bank Sta=69.6,87.9
XS Rating Curve= 0 ,0
Exp/Cntr=0.3,0.1

Type RM Length L Ch R = 1 ,4288    ,138.4,140.4,142.1
XS GIS Cut Line= 3
     1805748.052      290665.228     1805770.621      290694.742
     1805850.482      290759.846
#Sta/Elev= 30
       0 1662.74     7.4 1660.88    11.2 1660.06    22.3 1658.45      26  1657.7
    29.7 1656.16    33.4 1653.83    37.2 1651.72    41.1 1649.97    45.1 1647.62
      49 1645.22    51.7 1644.14      53 1643.62      57  1643.2    60.9 1643.07
    64.9 1643.51    68.9 1644.27    76.8 1646.63    80.8 1647.55    84.7 1648.16
    92.6 1648.77   100.6  1650.7   104.5 1651.79   108.5 1653.64   116.4  1658.9
   120.4 1661.72   128.3 1668.15   132.3 1671.24   136.2 1674.09   140.2 1676.75
#Mann= 3 , 0 , 0
       0      .1       0    51.7    .045       0    68.9      .1       0
Bank Sta=51.7,68.9
XS Rating Curve= 0 ,0
Exp/Cntr=0.3,0.1

Type RM Length L Ch R = 1 ,4147.6  ,128.3,130.4,131.2
XS GIS Cut Line= 2
     1805634.336      290752.902     1805752.392      290865.749
#Sta/Elev= 30
       0 1670.63       8    1665    15.9 1658.36    19.9 1655.21    23.9 1652.61
    27.9 1650.27    31.9 1648.24    35.8 1646.02    39.8 1643.49    43.8 1641.36
    47.8 1640.24    51.8 1639.95    55.8 1640.39    67.7 1643.01    71.7 1644.08
    75.7 1643.75    79.7 1641.37    83.6    1638    87.6 1636.96    91.6 1636.64
    95.6 1636.88    99.6 1637.92   107.6 1640.96   115.5 1644.29   119.5 1645.68
   123.5 1646.74   135.4 1651.92   143.4 1657.68   155.4 1663.86   163.3 1668.58
#Mann= 3 , 0 , 0
       0      .1       0    83.6    .045       0    99.6      .1       0
#XS Ineff= 2 , 0
           72.86 1652.45
Permanent Ineff=
       F       F
Bank Sta=83.6,99.6
XS Rating Curve= 0 ,0
Exp/Cntr=0.3,0.1

Type RM Length L Ch R = 1 ,4017.2  ,133,127.5,122.6
XS GIS Cut Line= 4
     1805549.267      290824.082     1805569.232        290856.2
     1805636.072      290930.853     1805685.552      290967.312
#Sta/Elev= 30
       0 1661.68    11.4 1654.06    26.5 1645.83    45.5 1637.26    49.4 1635.86
    53.8 1634.98    57.1 1634.55    68.6 1634.09    72.5 1634.16    76.4 1635.21
    80.2 1636.59    87.9 1638.91    91.8 1639.91    95.6 1640.34    99.5 1640.22
   107.2 1637.88     111 1637.15   114.9 1637.12   118.8 1638.36   126.5 1642.14
   130.3 1643.29     138 1645.11   145.7 1647.63   149.5 1649.19   153.4 1651.43
   161.1 1656.67   164.9 1659.54   176.4 1668.84     188 1676.85   199.5  1685.5
#Mann= 3 , 0 , 0
       0      .1       0    53.8    .045       0    72.5      .1       0
Bank Sta=53.8,72.5
XS Rating Curve= 0 ,0
Exp/Cntr=0.3,0.1

Type RM Length L Ch R = 1 ,3889.7  ,110.9,111.3,110.7
XS GIS Cut Line= 4
      1805449.44      290916.096      1805480.69      290950.819
     1805567.496      291009.846     1805608.295      291053.249
#Sta/Elev= 30
       0 1660.03     3.9 1657.56    27.2 1645.62    46.7  1634.8    50.6 1633.15
    54.5 1632.16    58.4 1631.89    66.2 1632.39    81.7 1631.85    85.3 1630.56
    89.5 1629.43    97.3 1629.03   101.1 1629.09     105 1630.08   108.9 1631.26
   112.8 1631.94   124.5 1632.37   132.2 1632.21   136.1 1632.49     140 1633.73
   151.7 1640.26   159.6 1644.29   167.6  1649.1   171.5 1652.26   183.5 1660.18
   187.4 1663.07   191.4 1665.64   199.3 1669.99   203.3 1672.84   211.3 1679.68
#Mann= 3 , 0 , 0
       0      .1       0    85.3    .045       0     105      .1       0
Bank Sta=85.3,105
XS Rating Curve= 0 ,0
Exp/Cntr=0.3,0.1

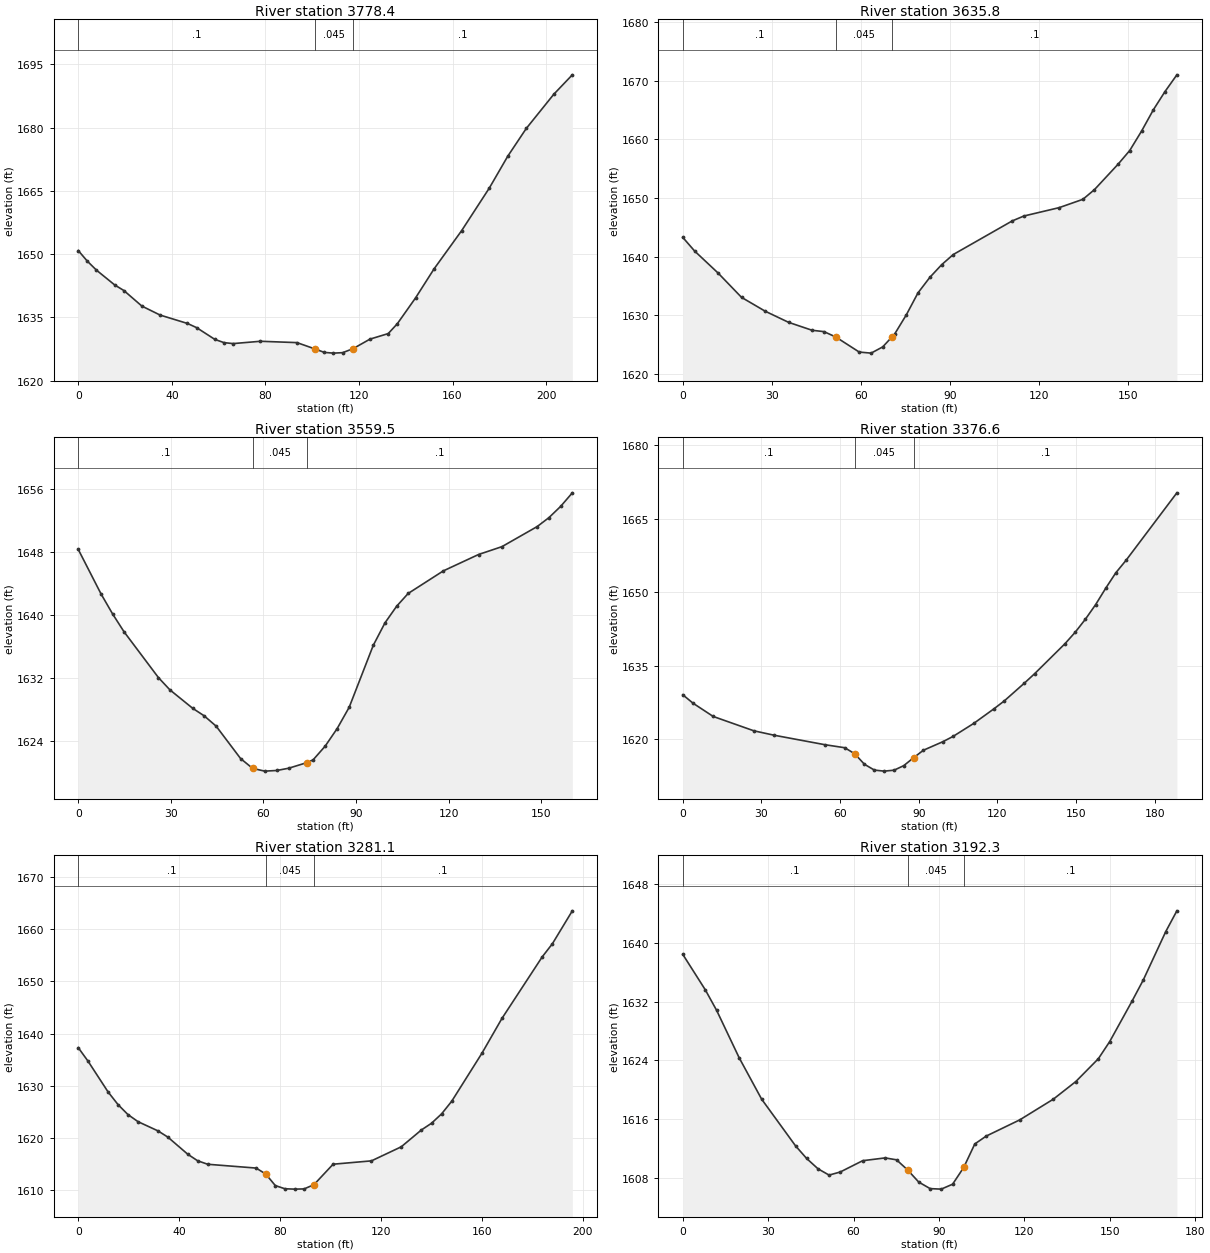
Type RM Length L Ch R = 1 ,3778.4  ,143.1,142.6,142.6
XS GIS Cut Line= 4
     1805402.565       291012.45     1805433.815      291047.173
     1805514.545       291101.86     1805564.024      291146.999
#Sta/Elev= 30
       0 1650.86     3.9 1648.34     7.8 1646.21    15.6  1642.7    19.5 1641.39
    27.2  1637.7      35 1635.57    46.7 1633.58    50.6 1632.59    58.4  1629.8
    62.3 1629.04    66.2 1628.81    77.9 1629.36    93.5 1629.04   101.3 1627.52
   105.2 1626.72   109.1 1626.55     113 1626.66   117.4 1627.58   124.7 1629.87
   132.5 1631.18   136.4 1633.52   144.2 1639.65   152.1 1646.52   163.9 1655.59
   175.7 1665.66   183.6 1673.22   191.5 1679.79   203.3 1687.92   211.2 1692.51
#Mann= 3 , 0 , 0
       0      .1       0   101.3    .045       0   117.4      .1       0
Bank Sta=101.3,117.4
XS Rating Curve= 0 ,0
Exp/Cntr=0.3,0.1

Type RM Length L Ch R = 1 ,3635.8  ,84,76.3,68.5
XS GIS Cut Line= 2
     1805337.461      291147.578      1805476.35      291239.592
#Sta/Elev= 30
       0 1643.27       4 1640.94    11.9 1637.19    19.8 1633.04    27.8 1630.67
    35.7 1628.77    43.6 1627.42    47.6 1627.19    51.6 1626.27    59.5  1623.7
    63.5 1623.52    67.4 1624.58    70.6 1626.32    71.4 1626.75    75.4 1630.08
    79.3  1633.8    83.3 1636.45    87.3 1638.62    91.2 1640.35   111.1 1646.09
     115 1646.92   126.9 1648.35   134.9 1649.77   138.8 1651.42   146.8 1655.78
   150.7  1658.1   154.7 1661.42   158.7 1665.08   162.6 1668.17   166.6 1671.02
#Mann= 3 , 0 , 0
       0      .1       0    51.6    .045       0    70.6      .1       0
Bank Sta=51.6,70.6
XS Rating Curve= 0 ,0
Exp/Cntr=0.3,0.1

Type RM Length L Ch R = 1 ,3559.5  ,180.8,182.9,182.8
XS GIS Cut Line= 4
     1805292.322      291214.707      1805324.44      291239.881
      1805373.92      291252.034     1805435.552      291281.548
#Sta/Elev= 30
       0 1648.35     7.4 1642.68    11.1 1640.17    14.8  1637.9      26 1632.05
    29.7  1630.5    37.1 1628.15    40.8  1627.2    44.7 1625.88    52.6 1621.77
    56.5 1620.52    60.4 1620.17    64.3 1620.25    68.2 1620.54      74 1621.24
    76.1  1621.6      80 1623.34    83.9 1625.58    87.8 1628.29    95.6 1636.16
    99.4 1639.02   103.2 1641.14   106.9 1642.75   118.3 1645.62   129.7  1647.7
   137.3  1648.7   148.7 1651.25   152.5 1652.38   156.3 1653.81   160.1 1655.54
#Mann= 3 , 0 , 0
       0      .1       0    56.5    .045       0      74      .1       0
Bank Sta=56.5,74
XS Rating Curve= 0 ,0
Exp/Cntr=0.3,0.1

Type RM Length L Ch R = 1 ,3376.6  ,91.6,95.5,100.9
XS GIS Cut Line= 4
     1805215.933       291378.77     1805265.413      291409.152
     1805305.343      291419.569     1805393.885      291429.985
#Sta/Elev= 30
       0 1629.06     3.9 1627.34    11.6 1624.63    27.1  1621.7    34.8  1620.8
    54.2 1618.86    61.8 1618.24    65.6    1617    69.3 1614.86    73.1 1613.67
    76.8 1613.46    80.6 1613.65    84.3 1614.58    88.1 1616.22    91.8 1617.73
    99.3 1619.49   103.2 1620.58     111 1623.21   118.7 1626.19   122.6 1627.78
   130.3 1631.43   134.2 1633.35   145.8 1639.49   149.7 1641.83   153.6  1644.5
   157.5 1647.48   161.4 1650.87   165.2 1653.98   169.1 1656.53   188.5 1670.32
#Mann= 3 , 0 , 0
       0      .1       0    65.6    .045       0    88.1      .1       0
Bank Sta=65.6,88.1
XS Rating Curve= 0 ,0
Exp/Cntr=0.3,0.1

Type RM Length L Ch R = 1 ,3281.1  ,91.5,88.8,86.1
XS GIS Cut Line= 4
     1805169.058      291451.687     1805213.329      291484.673
     1805270.621      291515.055     1805341.802      291541.096
#Sta/Elev= 30
       0 1637.33     3.9 1634.73    11.8 1628.87    15.8 1626.41    19.7 1624.52
    23.7 1623.16    31.6  1621.4    35.5 1620.21    43.4 1616.93    47.3 1615.68
    51.3 1615.01    70.5 1614.28    74.3 1613.14    78.1 1610.93    81.9 1610.32
    85.7 1610.25    89.5 1610.29    93.4  1611.1     101 1615.02   116.2 1615.66
     128 1618.35     136 1621.58     140 1622.86     144 1624.66     148 1627.07
     160 1636.28   167.9 1642.92   183.9 1654.73   187.9 1657.22   195.8 1663.52
#Mann= 3 , 0 , 0
       0      .1       0    74.3    .045       0    93.4      .1       0
Bank Sta=74.3,93.4
XS Rating Curve= 0 ,0
Exp/Cntr=0.3,0.1

Type RM Length L Ch R = 1 ,3192.3  ,108.1,115.5,123
XS GIS Cut Line= 3
     1805134.336        291543.7      1805163.85      291563.666
     1805292.322      291614.013
#Sta/Elev= 30
       0 1638.43     7.9 1633.61    11.9  1630.8    19.8 1624.36    27.7 1618.72
    39.6 1612.37    43.5 1610.65    47.5 1609.24    51.4 1608.38    55.3  1608.8
    63.2 1610.34    71.1 1610.72    75.1 1610.46      79 1609.08    82.9 1607.43
    86.9 1606.54    90.8 1606.47    94.8 1607.14    98.7 1609.42   102.6 1612.62
   106.6 1613.69   118.4  1615.9   130.2 1618.72   138.1 1621.12     146 1624.22
     150 1626.56   157.8 1632.03   161.8 1634.95   169.7 1641.54   173.6 1644.36
#Mann= 3 , 0 , 0
       0      .1       0      79    .045       0    98.7      .1       0
Bank Sta=79,98.7
XS Rating Curve= 0 ,0
Exp/Cntr=0.3,0.1

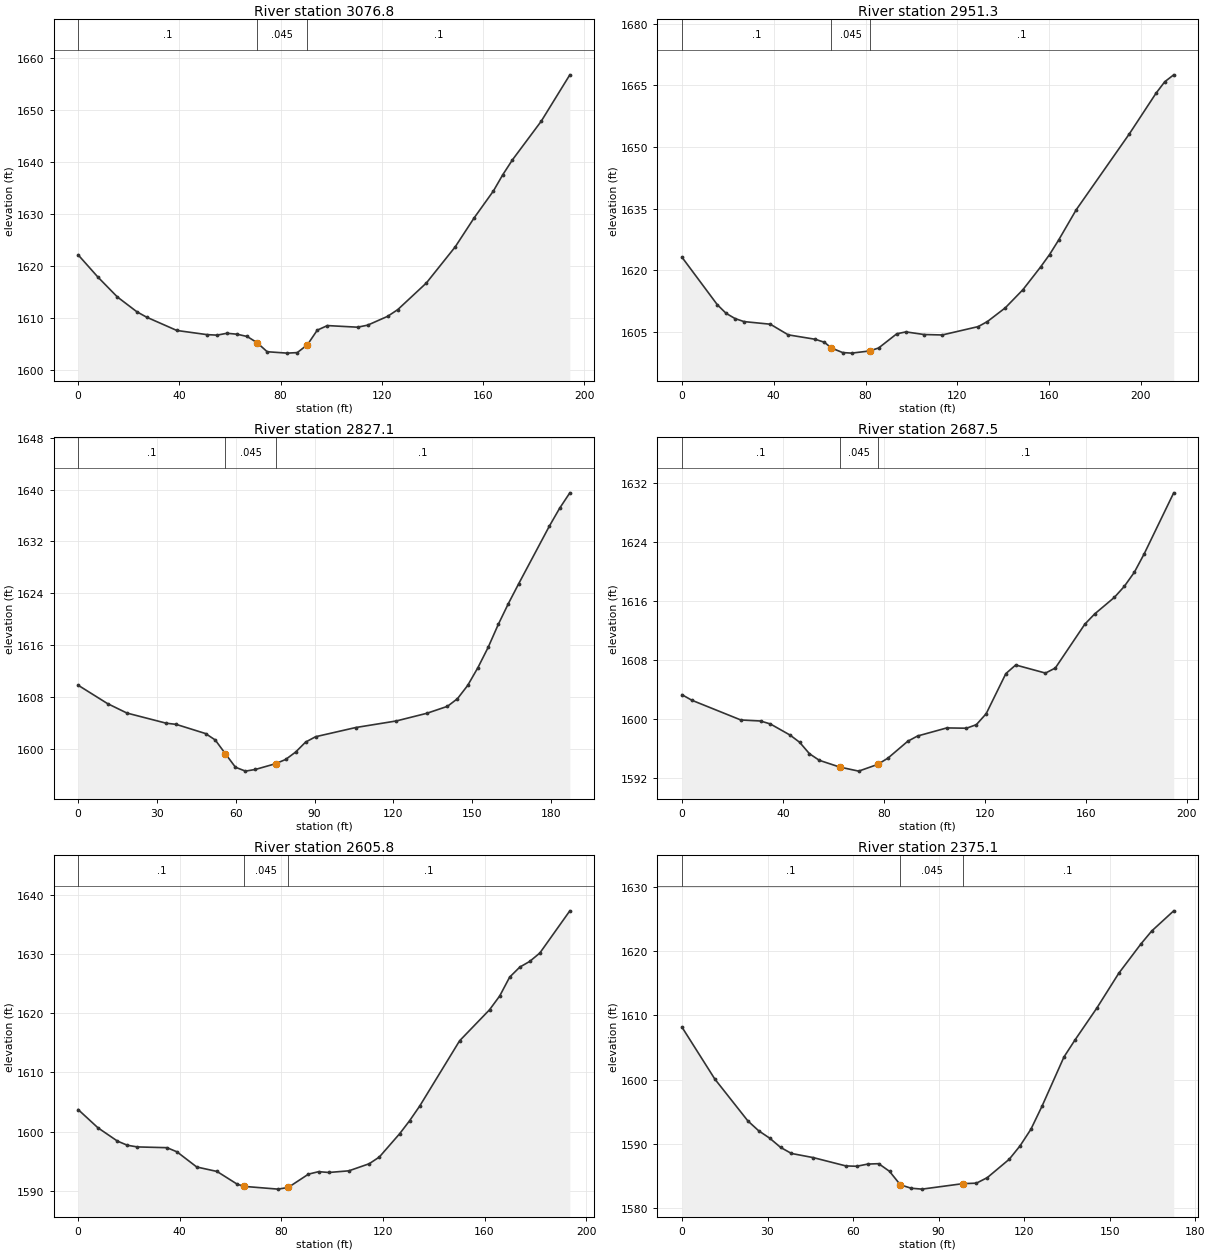
Type RM Length L Ch R = 1 ,3076.8  ,127.3,125.5,123.3
XS GIS Cut Line= 4
     1805103.954      291630.506     1805121.315      291651.339
     1805196.836      291715.575     1805255.864       291749.43
#Sta/Elev= 30
       0 1622.11     7.8 1617.84    15.5 1614.01    23.2 1611.16    27.1 1610.11
      39 1607.56    50.9 1606.76    54.9 1606.66    58.8 1607.02    62.8 1606.84
    66.8  1606.4    70.7 1605.22    74.7 1603.47    82.6  1603.2    86.6  1603.3
    90.6 1604.81    94.5 1607.62    98.5  1608.5   110.4 1608.19   114.4 1608.58
   122.3 1610.28   126.3 1611.57   137.6 1616.69     149 1623.64   156.5 1629.23
   164.1  1634.4   167.8 1637.52   171.6 1640.37     183 1647.82   194.3 1656.74
#Mann= 3 , 0 , 0
       0      .1       0    70.7    .045       0    90.6      .1       0
Bank Sta=70.7,90.6
XS Rating Curve= 0 ,0
Exp/Cntr=0.3,0.1

Type RM Length L Ch R = 1 ,2951.3  ,113.6,124.2,130.8
XS GIS Cut Line= 4
     1805023.225      291732.069     1805053.607      291761.582
     1805130.864       291816.27     1805195.968      291857.937
#Sta/Elev= 30
       0 1623.13    15.4 1611.57    19.2 1609.49    23.1 1608.21      27 1607.47
    38.5 1606.83    46.3 1604.24    58.1 1603.16    62.1 1602.42    65.1 1601.04
      70 1599.93    73.9 1599.79    81.8 1600.32    85.7 1601.05    93.6  1604.5
    97.6 1604.96   105.5 1604.32   113.4 1604.21   129.1 1606.25   133.1 1607.48
   140.9 1610.82   148.6 1615.25   156.3 1620.78   160.2  1623.8   164.1 1627.28
   171.8 1634.69     195 1653.21   206.6 1663.08   210.4 1665.87   214.3 1667.55
#Mann= 3 , 0 , 0
       0      .1       0    65.1    .045       0    81.8      .1       0
Bank Sta=65.1,81.8
XS Rating Curve= 0 ,0
Exp/Cntr=0.3,0.1

Type RM Length L Ch R = 1 ,2827.1  ,128.3,139.5,145.5
XS GIS Cut Line= 4
      1804972.01       291816.27     1804991.107      291864.881
     1805029.302      291912.624     1805060.552      291979.464
#Sta/Elev= 30
       0 1609.81    11.2 1606.97    18.6 1605.51    33.6 1603.94    37.3 1603.77
    48.5 1602.35    52.2 1601.36    56.1 1599.21    59.9 1597.15    63.7 1596.55
    67.5 1596.81    75.2  1597.7      79 1598.35    82.8 1599.49    86.6 1601.03
    90.4 1601.86   105.7 1603.28   121.1 1604.29   132.8 1605.48   140.6 1606.55
   144.4 1607.72   148.3 1609.77   152.2 1612.52   156.1 1615.65     160 1619.23
   163.8 1622.41   167.7 1625.45   179.4 1634.36   183.3 1637.11   187.2  1639.5
#Mann= 3 , 0 , 0
       0      .1       0    56.1    .045       0    75.2      .1       0
Bank Sta=56.1,75.2
XS Rating Curve= 0 ,0
Exp/Cntr=0.3,0.1

Type RM Length L Ch R = 1 ,2687.5  ,81.4,81.7,81.1
XS GIS Cut Line= 4
     1804886.072      291867.485     1804895.621      291909.152
     1804926.871      291980.332       1804945.1      292052.381
#Sta/Elev= 30
       0 1603.29     3.9 1602.54    23.3 1599.86    31.1 1599.72      35 1599.32
    42.8 1597.81    46.6 1596.83    50.5 1595.27    54.4 1594.38    62.5 1593.46
      70 1592.91    77.5 1593.82    81.6 1594.68    89.4 1596.96    93.3 1597.68
   104.9 1598.78   112.7 1598.74   116.6 1599.22   120.5 1600.71   128.3 1606.16
   132.2 1607.33     144 1606.23   147.9 1606.92   159.6 1612.88   163.5 1614.27
   171.3 1616.52   175.2    1618   179.2 1619.93   183.1 1622.43   194.8 1630.72
#Mann= 3 , 0 , 0
       0      .1       0    62.5    .045       0    77.5      .1       0
Bank Sta=62.5,77.5
XS Rating Curve= 0 ,0
Exp/Cntr=0.3,0.1

Type RM Length L Ch R = 1 ,2605.8  ,239.2,230.7,221.7
XS GIS Cut Line= 4
     1804819.232      291901.339     1804828.781      291943.006
     1804854.822      292018.527     1804873.052      292087.103
#Sta/Elev= 30
       0 1603.72     7.8 1600.63    15.5 1598.37    19.4 1597.67    23.3 1597.39
      35 1597.26    38.9 1596.56    46.7 1593.99    54.7 1593.23    62.7 1591.06
    65.5  1590.7    78.7 1590.24    82.7 1590.52    90.7 1592.78    94.7  1593.2
    98.7 1593.06   106.6 1593.34   114.6 1594.54   118.6 1595.68   126.6 1599.63
   130.5 1601.82   134.5 1604.32   150.2 1615.37     162 1620.63     166 1622.97
   169.9 1626.15   173.9 1627.85   177.8 1628.81   181.8 1630.24   193.6 1637.38
#Mann= 3 , 0 , 0
       0      .1       0    65.5    .045       0    82.7      .1       0
Bank Sta=65.5,82.7
XS Rating Curve= 0 ,0
Exp/Cntr=0.3,0.1

Type RM Length L Ch R = 1 ,2375.1  ,174.7,161.4,147.8
XS GIS Cut Line= 4
     1804604.822      292026.339     1804621.315      292061.062
     1804672.531      292122.694     1804702.045      292167.832
#Sta/Elev= 30
       0 1608.16    11.5  1600.1    23.1 1593.58    26.9 1592.04    30.8 1590.88
    34.6 1589.45    38.4 1588.51    46.1 1587.86    57.5 1586.57    61.3 1586.52
    65.2 1586.86      69 1586.92    72.8 1585.73    76.6 1583.63    80.4  1583.1
    84.2 1582.96    98.5 1583.81   103.3 1583.89   107.1 1584.75   114.8 1587.61
   118.6  1589.7   122.4 1592.28   126.3 1595.87     134 1603.53   137.8 1606.13
   145.5 1611.12   153.2 1616.54     161 1621.12   164.8 1623.14   172.5 1626.27
#Mann= 3 , 0 , 0
       0      .1       0    76.6    .045       0    98.5      .1       0
Bank Sta=76.6,98.5
XS Rating Curve= 0 ,0
Exp/Cntr=0.3,0.1

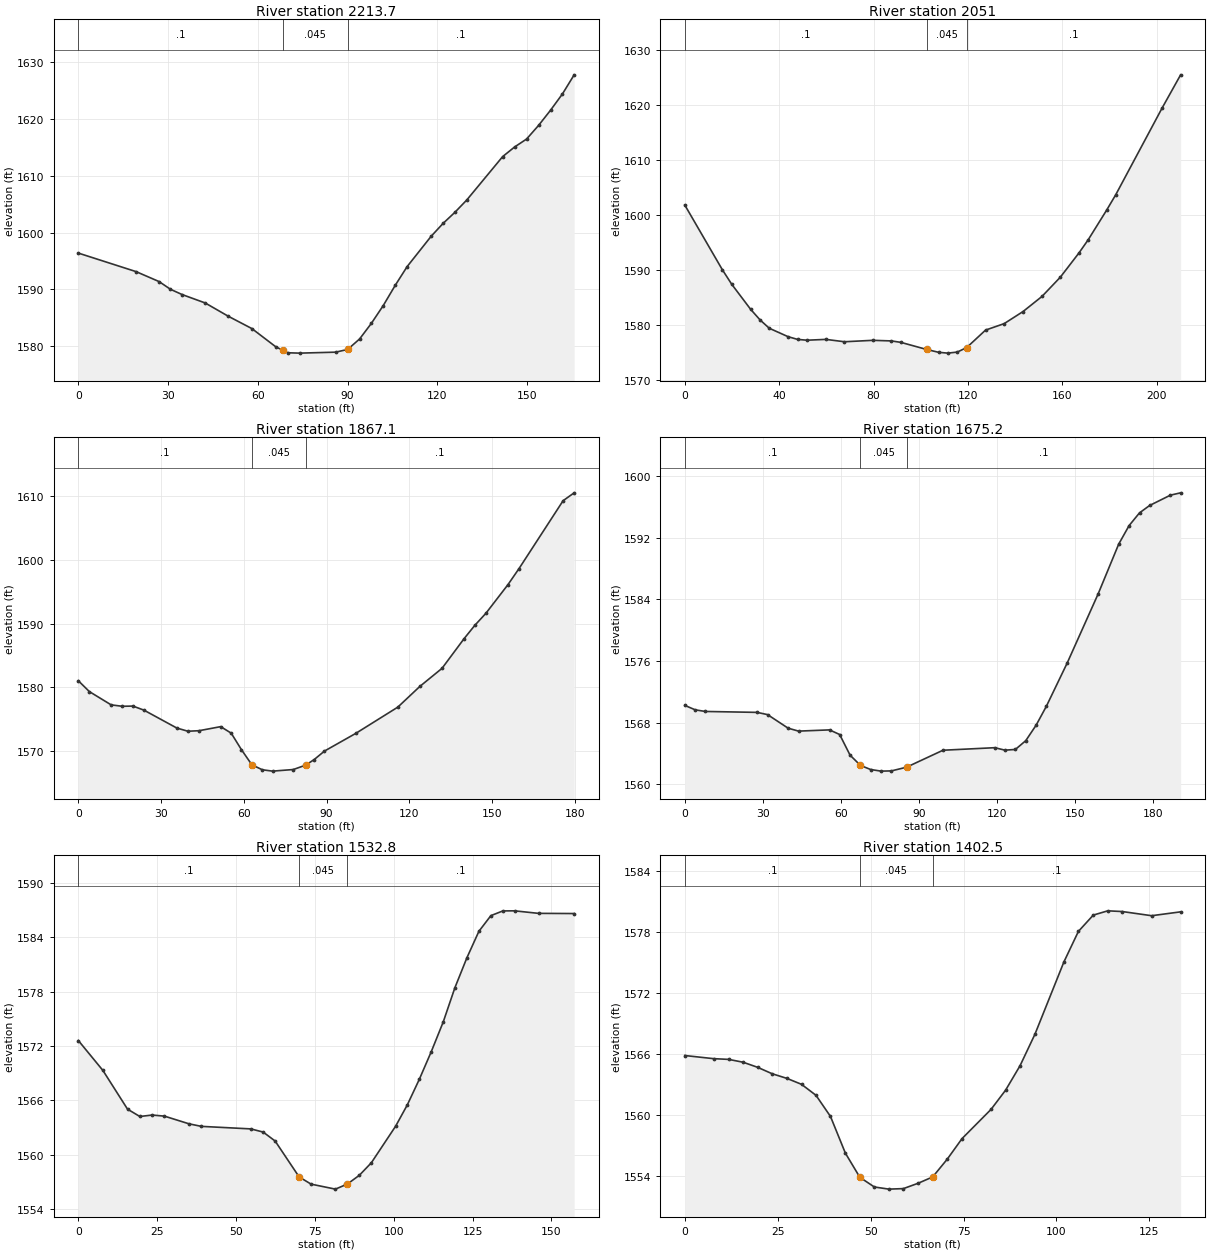
Type RM Length L Ch R = 1 ,2213.7  ,160.7,162.7,164.6
XS GIS Cut Line= 3
      1804511.94      292203.423     1804553.607        292231.2
     1804664.718      292263.319
#Sta/Elev= 30
       0 1596.37    19.3  1593.1      27 1591.34    30.8 1589.98    34.7 1589.05
    42.4 1587.57    50.1 1585.23      58 1583.05      66 1579.83    68.3 1579.23
      70 1578.78      74 1578.72      86 1578.89      90 1579.37      94 1581.22
    97.9 1583.95   101.9 1587.11   105.9 1590.68   109.9    1594   117.9 1599.33
   121.9 1601.61   125.8 1603.54   129.8 1605.73   141.8 1613.39   145.8 1615.09
   149.8 1616.49   153.8 1618.89   157.8 1621.57   161.8 1624.46   165.7 1627.82
#Mann= 3 , 0 , 0
       0      .1       0    68.3    .045       0      90      .1       0
Bank Sta=68.3,90
XS Rating Curve= 0 ,0
Exp/Cntr=0.3,0.1

Type RM Length L Ch R = 1 ,2051    ,173.9,183.9,193.8
XS GIS Cut Line= 4
     1804431.211      292355.332     1804468.538      292369.221
     1804572.704      292409.152     1804629.128      292425.645
#Sta/Elev= 30
       0  1601.8    15.9 1590.04    19.9 1587.38    27.9 1582.83    31.9  1580.9
    35.8 1579.38    43.8 1577.84    47.8 1577.35    51.8  1577.2    59.8 1577.35
    67.7 1576.92    79.7 1577.18    87.6 1577.07    91.6 1576.81   102.5 1575.52
   107.6    1575   111.5 1574.85   115.5 1575.04   119.5 1575.86   127.5 1579.04
   135.4 1580.22   143.4 1582.42   151.4 1585.16   159.2 1588.67   167.1 1593.08
     171 1595.47   178.8 1600.85   182.7 1603.68   202.3 1619.42   210.2  1625.5
#Mann= 3 , 0 , 0
       0      .1       0   102.5    .045       0   119.5      .1       0
Bank Sta=102.5,119.5
XS Rating Curve= 0 ,0
Exp/Cntr=0.3,0.1

Type RM Length L Ch R = 1 ,1867.1  ,181.5,191.9,205.3
XS GIS Cut Line= 4
     1804379.128      292490.749     1804417.322      292525.471
     1804458.989      292568.874     1804495.447      292626.166
#Sta/Elev= 30
       0 1581.05       4 1579.35    11.9 1577.27    15.9 1577.05    19.8 1577.08
    23.8 1576.44    35.7 1573.64    39.7 1573.14    43.7 1573.22    51.6 1573.86
    55.4 1572.84    59.1 1570.26    62.9 1567.88    66.7  1567.1    70.4 1566.89
    77.9 1567.14    82.4 1567.83    85.5 1568.71    89.2 1570.03   100.5 1572.79
   115.8 1576.92   123.8 1580.17   131.8 1582.99   139.8 1587.64   143.7 1589.73
   147.7 1591.61   155.7  1596.1   159.7 1598.61   175.7 1609.26   179.7 1610.49
#Mann= 3 , 0 , 0
       0      .1       0    62.9    .045       0    82.4      .1       0
Bank Sta=62.9,82.4
XS Rating Curve= 0 ,0
Exp/Cntr=0.3,0.1

Type RM Length L Ch R = 1 ,1675.2  ,141.4,142.4,138.8
XS GIS Cut Line= 2
       1804257.6      292586.235     1804320.968      292765.923
#Sta/Elev= 30
       0 1570.23       4 1569.65     7.9 1569.44    27.8 1569.32    31.8 1569.03
    39.7 1567.27    43.7 1566.89    55.6 1567.05    59.5 1566.45    63.5 1563.77
    67.5 1562.44    71.4 1561.91    75.4  1561.7    79.4 1561.73    85.2 1562.21
    99.2 1564.41   119.1 1564.74     123 1564.42     127 1564.51     131 1565.65
     135 1567.67   138.9  1570.1   146.9 1575.71   158.8 1584.68   166.7 1591.14
   170.7 1593.55   174.7  1595.2   178.6 1596.16   186.6  1597.5   190.5  1597.8
#Mann= 3 , 0 , 0
       0      .1       0    67.5    .045       0    85.2      .1       0
Bank Sta=67.5,85.2
XS Rating Curve= 0 ,0
Exp/Cntr=0.3,0.1

Type RM Length L Ch R = 1 ,1532.8  ,139.4,130.3,122.3
XS GIS Cut Line= 4
     1804149.961      292651.339     1804162.114      292708.631
     1804175.135      292748.562     1804189.892      292803.249
#Sta/Elev= 30
       0  1572.6     7.8 1569.29    15.6 1565.02    19.5 1564.21    23.4 1564.37
    27.3 1564.25    35.1  1563.4      39 1563.12    54.7 1562.84    58.6 1562.49
    62.4  1561.5      70 1557.54    73.8 1556.74    81.5 1556.19    85.3 1556.75
    89.1 1557.72    92.9  1559.1   100.6 1563.14   104.3 1565.49   108.1 1568.31
   111.9 1571.37   115.7 1574.66   119.4 1578.44   123.2 1581.74     127 1584.66
   130.8 1586.39   134.6 1586.91   138.3 1586.92   145.9 1586.64   157.2 1586.62
#Mann= 3 , 0 , 0
       0      .1       0      70    .045       0    85.3      .1       0
Bank Sta=70,85.3
XS Rating Curve= 0 ,0
Exp/Cntr=0.3,0.1

Type RM Length L Ch R = 1 ,1402.5  ,217.3,222.1,226.6
XS GIS Cut Line= 2
     1804022.357      292741.617      1804105.69      292845.784
#Sta/Elev= 30
       0 1565.85     7.8 1565.54    11.8 1565.47    15.7 1565.19    19.6 1564.69
    23.5 1564.06    27.5  1563.6    31.4 1563.02    35.3 1561.94    39.2 1559.86
    43.2 1556.26    47.1 1553.88      51 1552.93    54.9 1552.72    58.8 1552.77
    62.8  1553.3    66.7 1553.92    70.6 1555.66    74.6 1557.69    82.4 1560.56
    86.3 1562.44    90.2 1564.85    94.2 1567.94     102 1575.05   105.9 1578.05
   109.9 1579.65   113.8 1580.07   117.7    1580   125.6 1579.59   133.4 1579.97
#Mann= 3 , 0 , 0
       0      .1       0    47.1    .045       0    66.7      .1       0
Bank Sta=47.1,66.7
XS Rating Curve= 0 ,0
Exp/Cntr=0.3,0.1