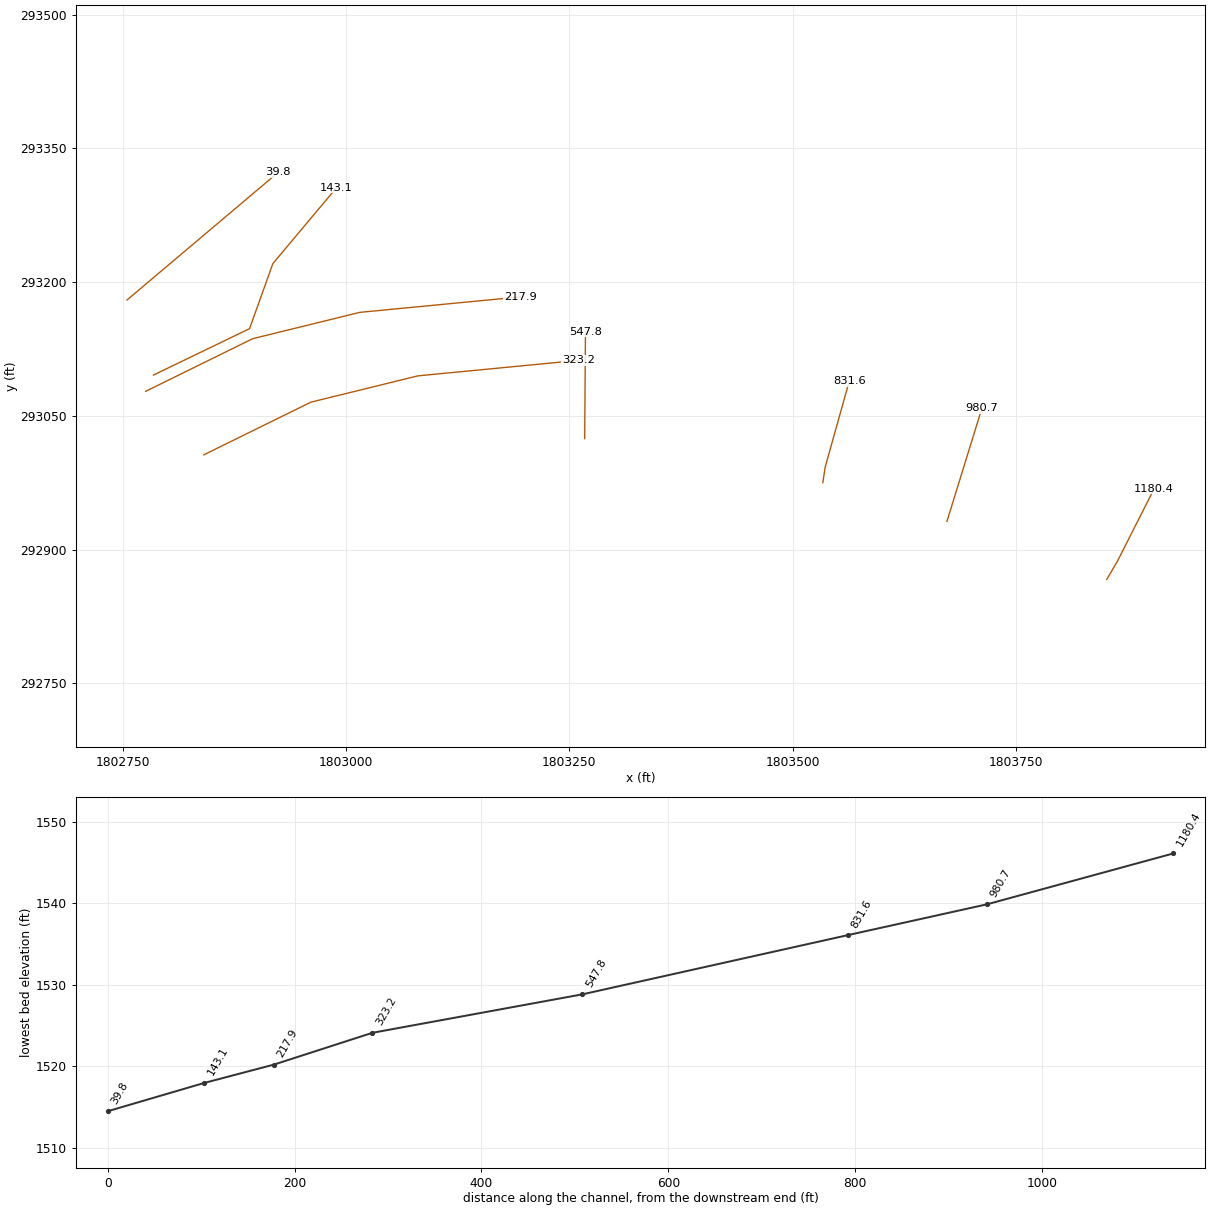
HEC-RAS study LACEYBR.prj: LACEYBR

--- LACEYBR.g01 (geometry) --- (continued)

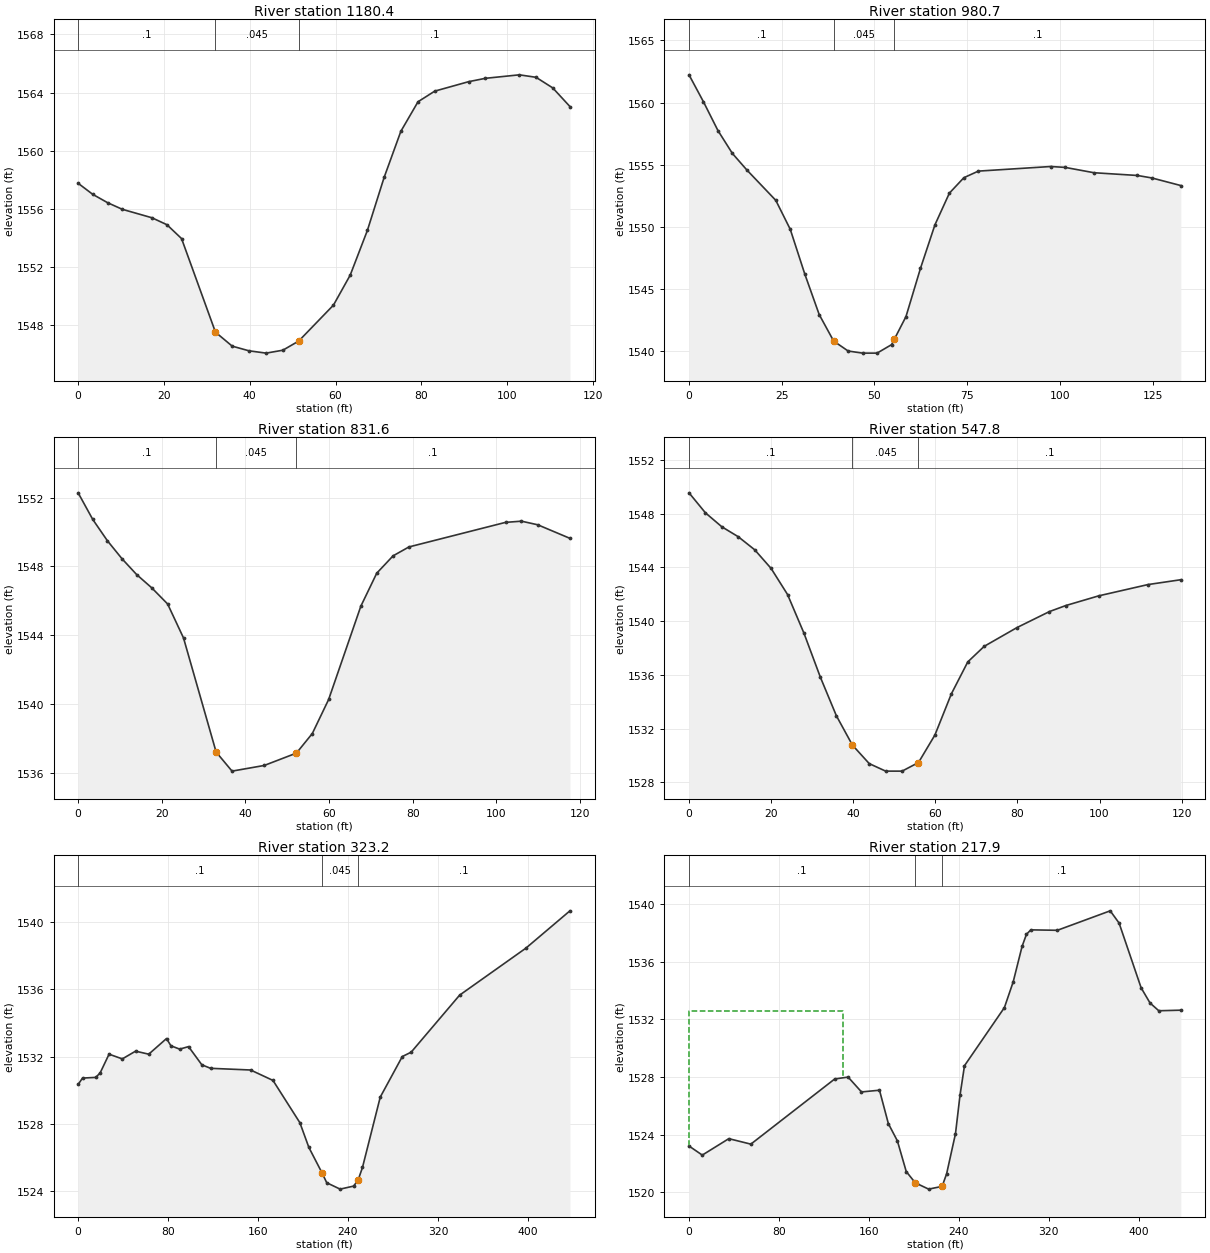
Type RM Length L Ch R = 1 ,1180.4  ,195.7,199.6,203.5
XS GIS Cut Line= 3
      1803851.35      292866.617     1803863.503       292887.45
     1803904.302       292968.18
#Sta/Elev= 26
       0 1557.77     3.4 1557.01     6.9 1556.43    10.3 1555.98    17.2  1555.4
    20.7 1554.92    24.1 1553.97      32 1547.54    35.9 1546.58    39.8 1546.26
    43.8  1546.1    47.7  1546.3    51.4 1546.93    59.5  1549.4    63.4 1551.46
    67.4 1554.53    71.3 1558.17    75.2 1561.34    79.2 1563.37    83.1  1564.1
      91 1564.75    94.9 1564.98   102.8 1565.22   106.7 1565.05   110.6 1564.32
   114.6 1563.04
#Mann= 3 , 0 , 0
       0      .1       0      32    .045       0    51.4      .1       0
Bank Sta=32,51.4
XS Rating Curve= 0 ,0
Exp/Cntr=0.3,0.1

Type RM Length L Ch R = 1 ,980.7   ,148.5,149.1,149.7
XS GIS Cut Line= 2
     1803672.531      292931.721     1803711.593      293058.457
#Sta/Elev= 27
       0 1562.23     3.9 1560.06     7.8 1557.75    11.7 1555.91    15.6 1554.58
    23.4 1552.14    27.3 1549.81    31.2 1546.23    35.1 1542.96      39 1540.83
    42.9 1540.03    46.8 1539.86    50.7 1539.86    54.6 1540.54    55.4    1541
    58.5  1542.8    62.4 1546.67    66.3 1550.17    70.2 1552.72    74.1 1553.96
      78 1554.49    97.5 1554.86   101.4 1554.79   109.2 1554.36   120.9 1554.14
   124.8 1553.94   132.6 1553.33
#Mann= 3 , 0 , 0
       0      .1       0      39    .045       0    55.4      .1       0
Bank Sta=39,55.4
XS Rating Curve= 0 ,0
Exp/Cntr=0.3,0.1

Type RM Length L Ch R = 1 ,831.6   ,278.2,283.9,289.4
XS GIS Cut Line= 3
     1803533.642      292975.124     1803536.246      292992.485
     1803563.156      293088.839
#Sta/Elev= 22
       0 1552.28     3.5 1550.73       7 1549.49    10.5 1548.44      14 1547.52
    17.6 1546.75    21.4 1545.81    25.2 1543.83      33 1537.19    36.8 1536.08
    44.5 1536.41    52.2 1537.13      56 1538.27    59.9 1540.25    67.6 1545.68
    71.4  1547.6    75.3 1548.61    79.1 1549.13   102.2 1550.56     106 1550.63
   109.9 1550.42   117.6 1549.63
#Mann= 3 , 0 , 0
       0      .1       0      33    .045       0    52.2      .1       0
Bank Sta=33,52.2
XS Rating Curve= 0 ,0
Exp/Cntr=0.3,0.1

Type RM Length L Ch R = 1 ,547.8   ,264.7,224.6,134.4
XS GIS Cut Line= 2
     1803267.149      293024.603     1803268.017      293144.395
#Sta/Elev= 25
       0 1549.55       4 1548.06       8 1547.02      12 1546.28      16 1545.31
      20 1543.92      24 1541.98      28  1539.1      32 1535.82    35.9 1532.95
    39.8 1530.77    43.9 1529.39    47.9 1528.83    51.9 1528.83    55.9 1529.47
    59.9 1531.52    63.9 1534.58    67.9 1536.96    71.9 1538.12    79.9 1539.52
    87.8 1540.71    91.8 1541.16    99.8 1541.88   111.8 1542.72   119.8 1543.08
#Mann= 3 , 0 , 0
       0      .1       0    39.8    .045       0    55.9      .1       0
Bank Sta=39.8,55.9
XS Rating Curve= 0 ,0
Exp/Cntr=0.3,0.1

Type RM Length L Ch R = 1 ,323.2   ,104.8,105.2,159.2
XS GIS Cut Line= 4
     1802840.933      293006.374     1802960.725      293065.402
     1803080.517      293094.916     1803260.204      293112.277
#Sta/Elev= 30
       0 1530.34     3.9 1530.72    15.7 1530.76    19.6 1531.03    27.5 1532.14
    39.3 1531.86    51.1 1532.32    62.8 1532.14    78.6 1533.07    82.5 1532.64
    90.3 1532.44    98.2 1532.59     110 1531.51   117.8  1531.3   153.4  1531.2
   173.3 1530.58   197.2 1528.07   205.2  1526.6   217.1 1525.06   221.1  1524.5
     233 1524.12     245  1524.3     249 1524.66   252.9 1525.41   268.7 1529.59
   288.3    1532   296.2 1532.26   339.3 1535.65   398.2 1538.44   437.4 1540.66
#Mann= 3 , 0 , 0
       0      .1       0   217.1    .045       0     249      .1       0
Bank Sta=217.1,249
XS Rating Curve= 0 ,0
Exp/Cntr=0.3,0.1

Type RM Length L Ch R = 1 ,217.9   ,43.3,74.9,102.8
XS GIS Cut Line= 4
     1802775.829      293077.555     1802895.621      293136.582
     1803015.413      293166.096       1803195.1      293183.457
#Sta/Elev= 30
       0 1523.22    11.8 1522.59    35.4 1523.73      55 1523.35   129.6 1527.87
   141.5    1528   153.4 1526.97   169.4 1527.09   177.3 1524.77   185.3 1523.58
   193.2 1521.45   201.2 1520.67   213.1 1520.23   225.1 1520.42   229.1 1521.29
     237 1524.08     241 1526.73     245 1528.79   280.5 1532.82   288.3  1534.6
   296.2 1537.06   300.1  1537.9     304 1538.21   327.6 1538.18   374.6 1539.53
   382.5 1538.68   402.1 1534.19     410 1533.14   417.8  1532.6   437.4 1532.64
#Mann= 3 , 0 , 0
       0      .1       0   201.2    .045       0   225.1      .1       0
#XS Ineff= 2 , 0
          137.29 1532.58
Permanent Ineff=
       F       F
Bank Sta=201.2,225.1
XS Rating Curve= 0 ,0
Exp/Cntr=0.3,0.1

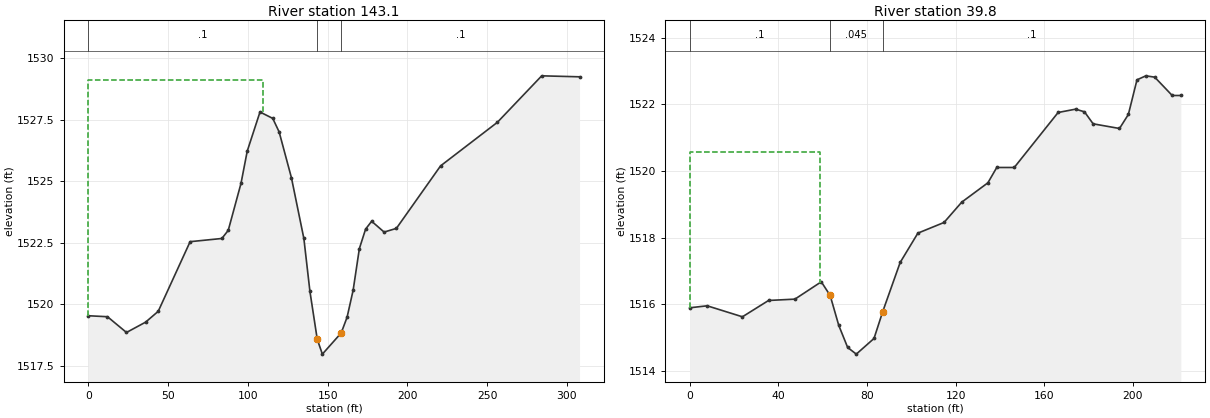
Type RM Length L Ch R = 1 ,143.1   ,115,103.2,91.1
XS GIS Cut Line= 4
      1802784.51      293095.784     1802892.149      293147.867
      1802918.19      293220.784     1802989.371      293305.853
#Sta/Elev= 30
       0 1519.53      12 1519.49    23.9 1518.85    35.9 1519.27    43.8 1519.71
    63.8 1522.54    83.7 1522.67    87.7    1523    95.7 1524.91    99.6 1526.22
   107.6 1527.81   115.6 1527.55   119.6    1527   127.3 1525.14   135.1 1522.67
   138.9 1520.52   143.5 1518.57   146.7 1517.97   158.5 1518.83   162.2 1519.47
     166 1520.57   169.9 1522.26   173.8 1523.05   177.6 1523.37   185.4 1522.93
   193.1 1523.08   220.8 1525.62   256.4 1527.39   284.2 1529.28   307.9 1529.24
#Mann= 3 , 0 , 0
       0      .1       0   143.5    .045       0   158.5      .1       0
#XS Ineff= 2 , 0
          109.43 1529.11
Permanent Ineff=
       F       F
Bank Sta=143.5,158.5
XS Rating Curve= 0 ,0
Exp/Cntr=0.3,0.1

Type RM Length L Ch R = 1 ,39.8    ,35.9,39.9,43.9
XS GIS Cut Line= 2
     1802754.996      293179.985     1802924.267      293323.214
#Sta/Elev= 30
       0  1515.9     7.9 1515.96    23.8 1515.63    35.6 1516.12    47.5 1516.16
    59.4 1516.68    63.4 1516.27    67.3 1515.37    71.3 1514.71    75.2 1514.51
    83.2 1514.98    87.1 1515.78      95 1517.26     103 1518.14   114.8 1518.46
   122.8 1519.07   134.6 1519.65   138.6 1520.11   146.5 1520.11   166.3 1521.76
   174.2 1521.86   178.2 1521.78   182.1 1521.42     194 1521.28     198  1521.7
   201.9 1522.74   205.9 1522.86   209.9 1522.82   217.8 1522.27   221.7 1522.27
#Mann= 3 , 0 , 0
       0      .1       0    63.4    .045       0    87.1      .1       0
#XS Ineff= 2 , 0
            58.9 1520.57
Permanent Ineff=
       F       F
Bank Sta=63.4,87.1
XS Rating Curve= 0 ,0
Exp/Cntr=0.3,0.1

Chan Stop Cuts=-1
Use User Specified Reach Order=0
Composite Channel Slope=5